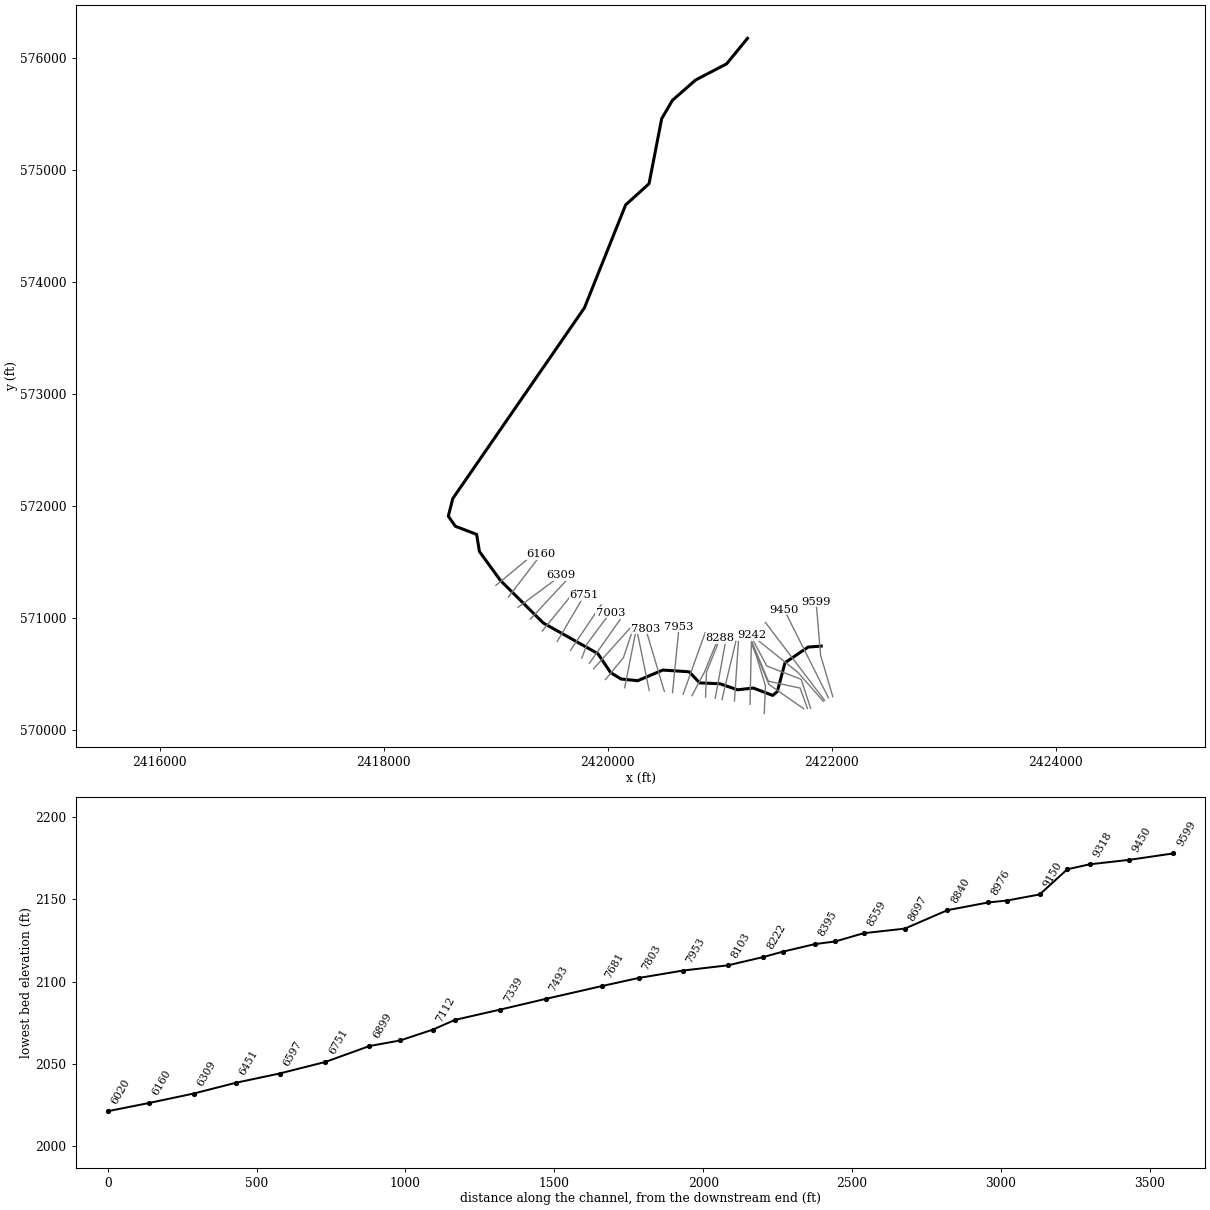
--- SBPOTOMC_T6.prj (project) ---

Proj Title=SBPOTOMC_T6
Current Plan=p01
Default Exp/Contr=0,0
English Units
Geom File=g01
Flow File=f01
Plan File=p01
BEGIN DESCRIPTION:
Stream Name: South Branch Potomac River  Tributary 6
Flood Zone: Approximate
Pendleton County, West Virginia
HEC-RAS Version: 5.0.7
Hydrology Method:
Regression equation
END DESCRIPTION:
DSS File=H:\CTP\WV\f03_Pendleton_RiskMAP\f05_Engineering\f02_Hydraulics\02_Final\Approximate\SBPOTOMC_T6\SBPOTOMC_T6.dss
DSS Export Rating Curves= 0
DSS Export Rating Curve Sorted= 0
DSS Export Volume Flow Curves= 0
DXF Filename=H:\CTP\WV\f03_Pendleton_RiskMAP\f05_Engineering\f02_Hydraulics\02_Final\Approximate\SBPOTOMC_T6\SBPOTOMC_T6.
DXF OffsetX= 0
DXF OffsetY= 0
DXF ScaleX= 0
DXF ScaleY= 0

--- SBPOTOMC_T6.p01 (plan) ---

Plan Title=Floodplain
Program Version=5.07
Short Identifier=Floodplain
Geom File=g01
Flow File=f01
Subcritical Flow
K Sum by GR= 0
Std Step Tol= 0.01
Critical Tol= 0.01
Num of Std Step Trials= 20
Max Error Tol= 0.3
Flow Tol Ratio= 0.001
Split Flow NTrial= 30
Split Flow Tol= 0.02
Split Flow Ratio= 0.02
Log Output Level= 0
Friction Slope Method= 1
Unsteady Friction Slope Method= 2
Unsteady Bridges Friction Slope Method= 1
Parabolic Critical Depth
Global Vel Dist= 0 , 0 , 0
Global Log Level= 0
CheckData=True
Encroach Param=-1 ,0,0, 0
Computation Interval=0.1SEC
Output Interval=1MIN
Instantaneous Interval=Max Profile
Mapping Interval=1HOUR
Computation Time Step Use Courant=        0
Computation Time Step Use Time Series=    0
Computation Time Step Count To Double=0
Computation Time Step Max Doubling=0
Computation Time Step Max Halving=0
Computation Time Step Residence Courant=0
Run HTab= 0
Run UNet= 0
Run Sediment= 0
Run PostProcess= 0
Run WQNet= 0
Run RASMapper= 0
UNET Theta= 0
UNET Theta Warmup= 0
UNET ZTol= 0
UNET ZSATol= 0
UNET MxIter= 0
UNET Max Iter WO Improvement= 0
UNET MaxInSteps= 0
UNET DtIC= 0
UNET DtMin= 0
UNET MaxCRTS= 0
UNET WFStab= 0
UNET SFStab= 0
UNET WFX= 1
UNET SFX= 1
UNET 1D Methodology=Finite Difference
UNET DSS MLevel= 1
UNET Pardiso=0
UNET DZMax Abort= 0
UNET Use Existing IB Tables= 0
UNET Froude Reduction=False
UNET Froude Limit= 0
UNET Froude Power= 0
UNET D1 Cores= 0
UNET D2 Coriolis=0
UNET D2 Cores= 0
UNET D2 Theta= 1
UNET D2 Theta Warmup= 1
UNET D2 Z Tol= 0.01
UNET D2 Volume Tol= 0.01
UNET D2 Max Iterations= 20
UNET D2 Equation= 0
UNET D2 RampUpFraction=0.1
UNET D2 TimeSlices= 1
UNET D2 BCVolumeCheck=0
UNET D1D2 MaxIter= 0
UNET D1D2 ZTol=0.01
UNET D1D2 QTol=0.1
UNET D1D2 MinQTol=1
DSS File=dss
Write IC File= 0
Write IC File at Fixed DateTime=0
Write IC File at Sim End=0
Echo Input=False
Echo Parameters=False
Echo Output=False
Write Detailed= 0
HDF Write Warmup=0
HDF Write Time Slices=0
HDF Flush=0
HDF Face Node Velocities=0
HDF Compression= 1
HDF Chunk Size= 1
HDF Spatial Parts= 1
HDF Use Max Rows=0
HDF Fixed Rows= 1
Calibration Method= 0
Calibration Iterations= 20
Calibration Max Change=0.05
Calibration Tolerance=0.2
Calibration Maximum=1.5
Calibration Minimum=0.5
Calibration Optimization Method= 1
WQ AD Non Conservative
WQ ULTIMATE=-1
WQ Max Comp Step=1HOUR
WQ Output Interval=15MIN
WQ Output Selected Increments= 0
WQ Output face flow=0
WQ Output face velocity=0
WQ Output face area=0
WQ Output face dispersion=0
WQ Output cell volume=0
WQ Output cell surface area=0
WQ Output cell continuity=0
WQ Output cumulative cell continuity=0
WQ Output face conc=0
WQ Output face dconc_dx=0
WQ Output face courant=0
WQ Output face peclet=0
WQ Output face adv mass=0
WQ Output face disp mass=0
WQ Output cell mass=0
WQ Output cell source sink temp=0
WQ Output nsm pathways=0
WQ Output nsm derived pathways=0
WQ Output MaxMinRange=-1
WQ Daily Max Min Mean=-1
WQ Daily Range=0
WQ Daily Time=0
WQ Create Restart=0
WQ Fixed Restart=0
WQ System Summary=0
WQ Write To DSS=0
WQ Use Fixed Temperature=0
Sorting and Armoring Iterations= 10
XS Update Threshold= 0.02
Bed Roughness Predictor= 0
Hydraulics Update Threshold= 0.02
Energy Slope Method= 1
Volume Change Method= 1
Sediment Retention Method= 0
XS Weighting Method= 0
Number of US Weighted Cross Sections= 1
Number of DS Weighted Cross Sections= 1
Upstream XS Weight=0
Main XS Weight=1
Downstream XS Weight=0
Number of DS XS's Weighted with US Boundary= 1
Upstream Boundary Weight= 1
Weight of XSs Associated with US Boundary= 0
Number of US XS's Weighted with DS Boundary= 1
Downstream Boundary Weight= 0.5
Weight of XSs Associated with DS Boundary= 0.5
Percentile Method= 0
Sediment Output Level= 3
Mass or Volume Output= 0
Output Increment Type= 1
Profile and TS Output Increment= 1
XS Output Flag= 0
XS Output Increment= 10
Write Gradation File= 0
Read Gradation Hotstart= 0
Write HDF5 File= 1
Write Binary Output= 1
Write DSS Sediment File= 0
SV Curve= 0
Specific Gage Flag= 0

--- SBPOTOMC_T6.f01 (steady flow) ---

Flow Title=Flows
Program Version=5.07
Number of Profiles= 6
Profile Names=P100yr,P10yr,P25yr,P50yr,P500yr,P101yr
River Rch & RM=SBPOTOMC_T6,Main            ,9599
     745     347     491     614    1094     906
River Rch & RM=SBPOTOMC_T6,Main            ,5554
     829     386     546     683    1219    1008
Boundary for River Rch & Prof#=SBPOTOMC_T6,Main            , 1
Up Type= 0
Dn Type= 3
Dn Slope=0.02472
Boundary for River Rch & Prof#=SBPOTOMC_T6,Main            , 2
Up Type= 0
Dn Type= 3
Dn Slope=0.02472
Boundary for River Rch & Prof#=SBPOTOMC_T6,Main            , 3
Up Type= 0
Dn Type= 3
Dn Slope=0.02472
Boundary for River Rch & Prof#=SBPOTOMC_T6,Main            , 4
Up Type= 0
Dn Type= 3
Dn Slope=0.02472
Boundary for River Rch & Prof#=SBPOTOMC_T6,Main            , 5
Up Type= 0
Dn Type= 3
Dn Slope=0.02472
Boundary for River Rch & Prof#=SBPOTOMC_T6,Main            , 6
Up Type= 0
Dn Type= 3
Dn Slope=0.02472
DSS Import GetInterval= 0
DSS Import GetPeak= 0
DSS Import FillOption= 0

--- SBPOTOMC_T6.g01 (geometry) ---

Geom Title=Geometry
Program Version=5.07

River Reach=SBPOTOMC_T6     ,Main
Reach XY= 30
2421904.96200004570750.8299999982421788.09200001570742.495000005
2421581.79400003570602.6149999952421512.89500001570344.867000014
2421471.99399999 570310.939000012421299.20199999570376.694000006
2421158.74800003570361.0849999932420999.84400001570415.214000016
2420820.05400002570422.394999996      2420726.66570521.724999994
2420491.03400004570537.1510000082420267.17300004570442.187000006
      2420117.97570457.4170000112420025.31800002570514.925000012
2419910.96500003570684.2839999942419423.38400003570957.989999995
     2419041.204571338.0030000212418854.36300001571595.317000002
2418829.62000003571748.1060000062418639.26199999571820.824000016
2418576.63600004571910.9270000162418616.79800004 572068.14200002
2419791.88299999573770.5750000182420159.65000004574689.013000011
2420368.22799999574877.8170000022420480.98500004575457.792999998
2420576.13000003575621.3410000212420782.15200001 575802.57100001
2421061.12099999575948.1580000222421247.06765506576175.498034254

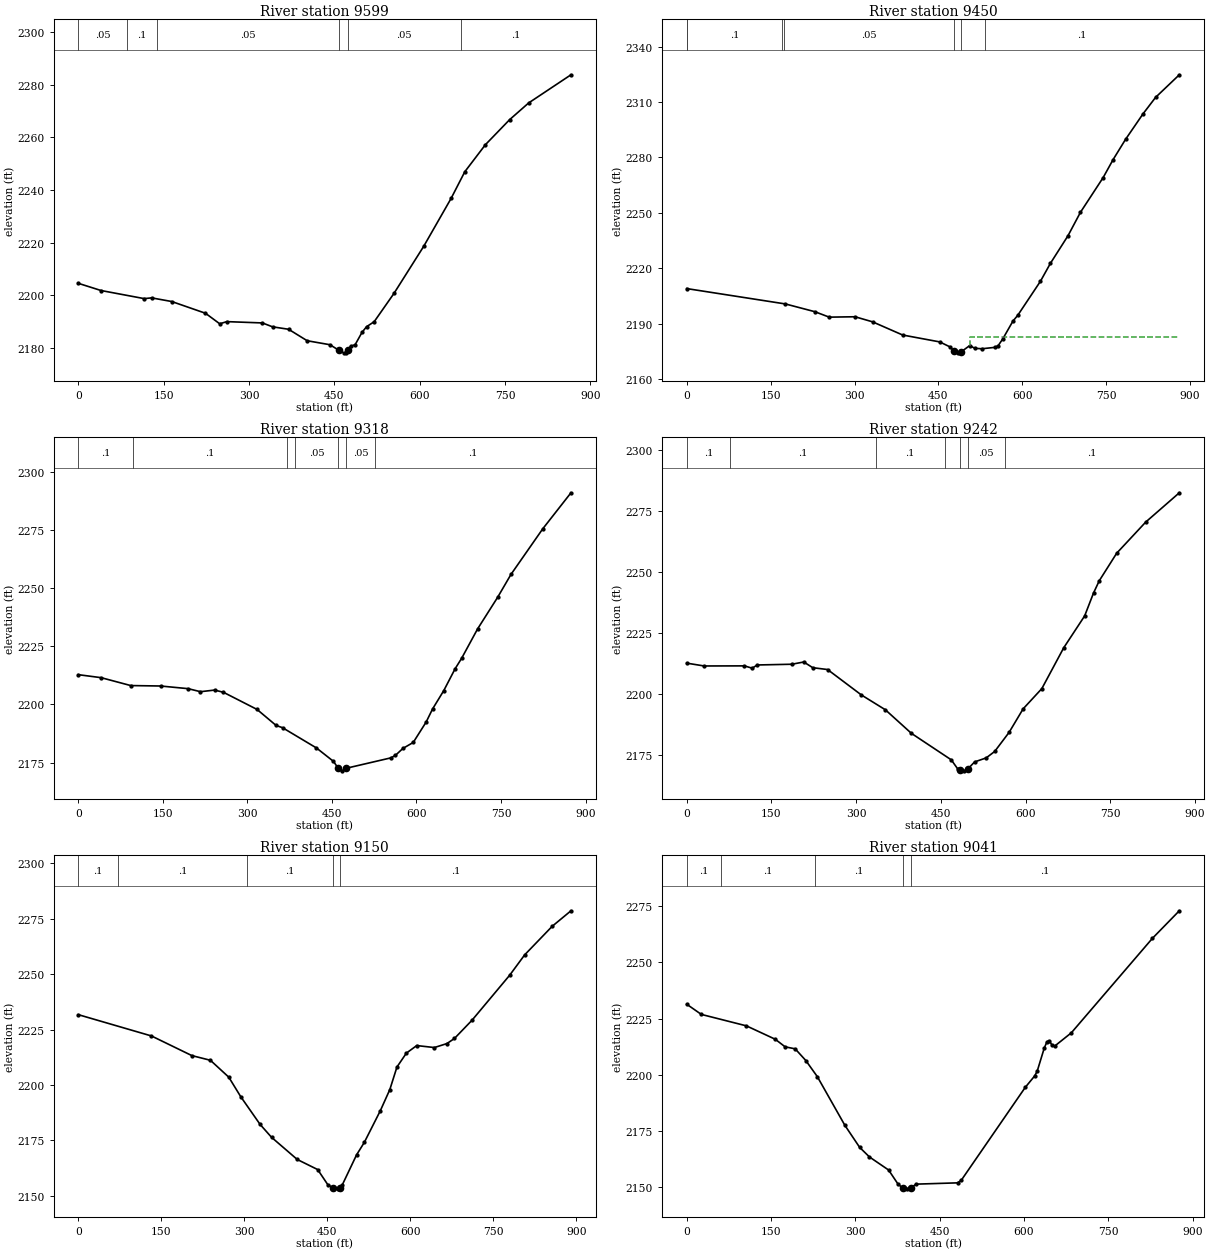
Type RM Length L Ch R = 1 ,9599    ,145.3,149.4,153.8
XS GIS Cut Line= 3
     2422008.244      570300.576  2421899.512928570669.531296087
     2421859.206      571148.858
#Sta/Elev= 30
       0 2204.49    39.9 2201.76   115.8 2198.68   128.7 2198.97   164.1 2197.58
   223.4 2193.12   248.4 2189.12     261 2189.94   323.5 2189.44   341.3 2187.96
   369.4 2187.04   402.1 2182.68   442.2 2181.16   458.2    2179   466.3 2178.08
   470.3 2178.18   473.22179.126   478.3 2180.55   486.4 2181.18   498.4 2185.83
   506.4    2188   519.9 2189.92   554.6 2200.65   606.8 2218.52     655 2236.75
   679.1 2246.89   715.2 2257.14   757.8 2266.67   791.4 2273.05   865.7 2283.74
#Mann= 6 ,-1 , 0
       0     .05       0   86.33      .1       0  137.93     .05       0
   458.2    .045       0   473.2     .05       0  671.96      .1       0
Bank Sta=458.2,473.2
XS Rating Curve= 0 ,0
Exp/Cntr=0.3,0.1

Type RM Length L Ch R = 1 ,9450    ,130.2,131.8,133.5
XS GIS Cut Line= 2
     2421969.216      570289.958     2421573.601      571076.854
#Sta/Elev= 30
       0 2208.93   176.6  2200.6     229 2196.42   254.8 2193.46     301 2193.67
   332.3 2190.92   386.1 2183.78   452.4 2180.05   471.1 2177.29   478.22174.927
   484.6 2174.13   490.52174.658     506 2178.06     515 2176.59   527.8 2176.34
   551.7 2177.12   556.7 2177.95   565.2 2181.74   583.1 2191.25     592 2194.52
   632.3 2212.83   650.2 2222.58   681.6 2237.51   703.9 2250.22   744.4 2268.98
   762.4 2278.82   784.5 2289.71   815.9  2303.6   838.3 2312.49   880.7 2324.72
#Mann= 7 ,-1 , 0
       0     .05       0     .88      .1       0  170.25      .1       0
  173.53     .05       0   478.2    .045       0   490.5     .05       0
  533.01      .1       0
#XS Ineff= 2 , 0
                          506.18         2182.87
Permanent Ineff=
       F       F
Bank Sta=478.2,490.5
XS Rating Curve= 0 ,0
Exp/Cntr=0.3,0.1

Type RM Length L Ch R = 1 ,9318    ,75.9,75.4,79.9
XS GIS Cut Line= 2
     2421934.903      570266.305     2421406.434      570962.724
#Sta/Elev= 30
       0  2212.8    40.5 2211.51    92.9 2208.12   145.8 2207.93   194.7 2206.79
   216.7 2205.48   241.8 2206.18   257.5 2205.22   317.1 2197.85     351 2190.95
   362.3    2190   422.5 2181.28   452.7 2175.52   460.62172.749   467.7 2171.44
   475.82172.573   554.4 2177.01   562.7 2178.11   575.9 2181.07   594.3 2183.66
   617.2 2192.44   628.6 2198.06   648.5 2205.97   668.5 2215.31     680 2219.78
   708.5  2232.5   743.9 2246.02   767.8 2255.96   824.2 2275.57   874.2 2291.04
#Mann= 7 ,-1 , 0
       0      .1       0   96.31      .1       0  370.59      .1       0
   385.1     .05       0   460.6    .045       0   475.8     .05       0
  525.56      .1       0
Bank Sta=460.6,475.8
XS Rating Curve= 0 ,0
Exp/Cntr=0.3,0.1

Type RM Length L Ch R = 1 ,9242    ,91,92.5,96.9
XS GIS Cut Line= 3
2421923.11426132570259.0056447472421699.17083756570514.511564474
  2421284.349462570848.172236118
#Sta/Elev= 30
       0 2212.57    30.9 2211.41   102.2 2211.45   115.9  2210.5   124.9 2211.82
     186 2212.12   207.3 2213.04   223.2  2210.7   249.4 2209.95   309.1 2199.54
   351.7 2193.44   397.8 2183.77   468.4  2172.9   479.7 2169.21   484.42168.763
   491.1 2168.39   497.2 2169.04   509.7 2172.05   530.2  2173.7   545.2 2176.33
   570.8 2184.19   595.6 2193.82   628.7 2202.12   667.5 2218.89   704.5 2231.94
   720.2 2241.33   730.4 2246.38   761.2 2257.66   812.6 2270.44   872.1 2282.46
#Mann= 7 ,-1 , 0
       0      .1       0   76.89      .1       0  334.52      .1       0
  456.48     .05       0   484.4    .045       0   497.2     .05       0
  563.57      .1       0
Bank Sta=484.4,497.2
XS Rating Curve= 0 ,0
Exp/Cntr(USF)=0,0
Exp/Cntr=0.3,0.1

Type RM Length L Ch R = 1 ,9150    ,107.4,109.4,110.5
XS GIS Cut Line= 4
2421810.39106144570195.8806528152421726.22440553570454.392524538
2421419.61730186570573.127628412  2421282.846486570828.633548139
#Sta/Elev= 30
       0 2231.69   132.2 2222.08   205.2 2213.22   238.7 2211.11   271.9 2203.49
   293.5 2194.69   328.6 2182.14   349.2 2176.35   395.7 2166.34   432.6 2161.79
   451.2 2154.86   459.62153.663   468.6 2153.09   472.7 2153.49   477.2 2154.92
   502.9 2168.41   516.9 2174.05   545.8 2188.31     563 2197.87   575.9 2208.06
     593 2214.35   611.7 2217.75   643.5 2216.86   666.2 2218.64   679.8 2220.94
   711.6 2229.18   779.6 2249.47   806.8 2258.69   856.7 2271.61   890.5 2278.58
#Mann= 5 ,-1 , 0
       0      .1       0   71.21      .1       0  304.88      .1       0
   459.6    .045       0   472.7      .1       0
Bank Sta=459.6,472.7
XS Rating Curve= 0 ,0
Exp/Cntr(USF)=0,0
Exp/Cntr=0.3,0.1

Type RM Length L Ch R = 1 ,9041    ,68.8,64.1,59.8
XS GIS Cut Line= 4
2421781.83451747570194.3776768162421717.20654954570376.237772622
2421433.14408584570437.859788556   2421281.34351570800.077004169
#Sta/Elev= 30
       0 2231.36      26 2226.83   106.2 2221.75   157.6 2215.79   175.1 2212.43
     193 2211.54   211.9 2206.36   232.4 2199.19   281.4 2177.58   307.7 2167.79
   325.1 2163.54   359.2 2157.74   375.6 2151.62   384.22149.696   391.4 2149.38
   399.22149.955   408.4 2151.47     482 2152.04   488.6 2153.23   602.4 2194.46
   619.2 2199.55   623.6 2201.65     636 2211.79   640.9  2214.7   645.3 2215.08
   649.6  2213.3   654.4  2212.7   684.3 2218.66   828.6 2260.62   876.4 2272.84
#Mann= 5 ,-1 , 0
       0      .1       0   61.26      .1       0  228.95      .1       0
   384.2    .045       0   399.2      .1       0
Bank Sta=384.2,399.2
XS Rating Curve= 0 ,0
Exp/Cntr(USF)=0,0
Exp/Cntr=0.3,0.1

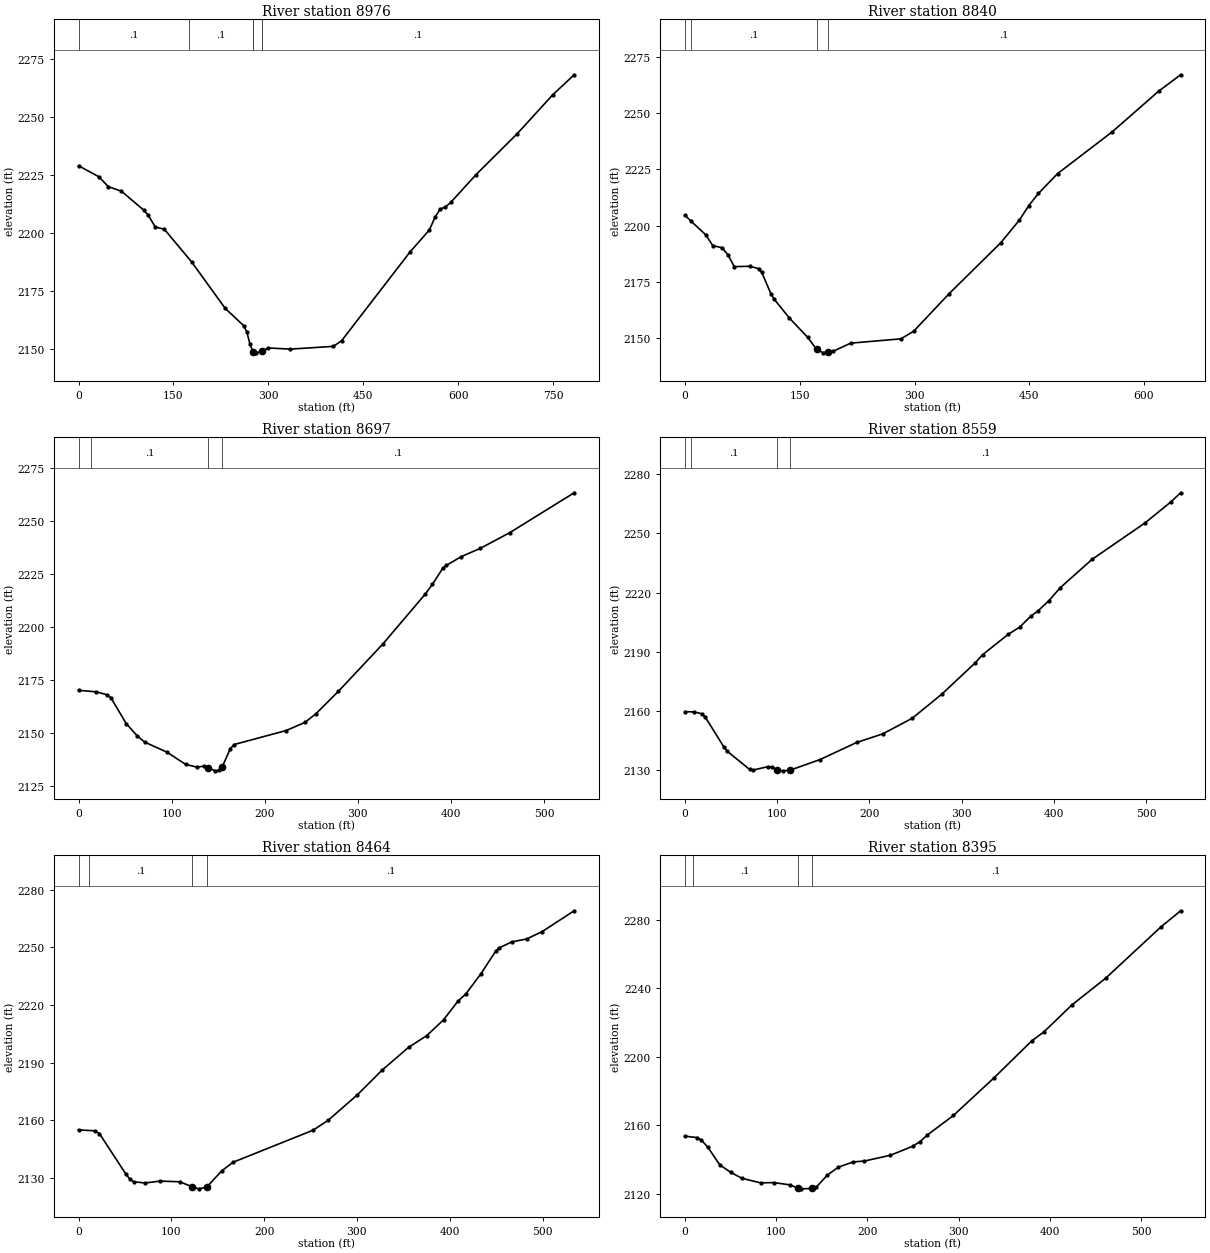
Type RM Length L Ch R = 1 ,8976    ,148.2,136.1,127.3
XS GIS Cut Line= 3
2421748.76048842570191.9854729292421438.14544875570409.082006032
 2421283.2003649570782.221137811
#Sta/Elev= 30
       0 2228.94    32.3 2224.16      47 2219.93    67.9 2217.92   102.8 2209.83
   109.8 2207.72   121.3  2202.5   135.7 2201.49   178.8 2187.38   231.8 2167.35
   261.1 2159.86     266  2157.1   270.9 2151.89   275.62148.725   280.6 2148.18
   289.72148.853   300.1 2150.29   334.3 2149.78   402.6 2150.98   415.6 2153.39
   523.8 2191.76   554.2 2201.19   563.5 2206.87   571.5 2210.31   578.8 2210.98
     588 2213.08   627.8 2225.05   692.8 2242.69   749.1 2259.53     783 2268.19
#Mann= 6 ,-1 , 0
       0      .1       0  174.52      .1       0  275.57      .1       0
   275.6    .045       0   289.7      .1       0  289.74      .1       0
Bank Sta=275.6,289.7
XS Rating Curve= 0 ,0
Exp/Cntr(USF)=0,0
Exp/Cntr=0.3,0.1

Type RM Length L Ch R = 1 ,8840    ,142.5,143.4,143.2
XS GIS Cut Line= 4
2421396.33845966570150.6028480692421407.68931757570395.069220496
 2421324.7783628570667.575742596   2421281.34351570777.532364193
#Sta/Elev= 30
       0 2204.63     8.3 2201.88    27.2 2195.91    36.3 2191.13    48.5  2190.2
    56.3 2186.99    64.4  2181.8    84.4 2181.95    96.4 2180.91   100.4 2179.22
   112.4 2169.68   116.4 2167.42   136.4 2158.98   160.5 2150.34   171.9 2145.07
   180.5  2143.5   186.5 2143.98   193.9 2144.23   216.5  2147.8   282.2 2149.72
   298.9 2153.09   345.2 2169.78   412.9 2192.47   436.9 2202.41   449.4 2208.94
     462 2214.32     487 2223.13   558.4 2241.68   619.1 2259.75   647.8 2267.03
#Mann= 4 ,-1 , 0
       0     .06       0     8.3      .1       0   171.9    .045       0
   186.5      .1       0
Bank Sta=171.9,186.5
XS Rating Curve= 0 ,0
Exp/Cntr(USF)=0,0
Exp/Cntr=0.3,0.1

Type RM Length L Ch R = 1 ,8697    ,138.3,138.3,137.4
XS GIS Cut Line= 2
2421269.31970202570231.952076776   2421281.34351570764.005580208
#Sta/Elev= 30
       0 2170.23    18.9 2169.53    30.9  2168.1    34.9 2166.66    51.2 2154.56
      63 2148.75    71.1 2145.79      95 2141.05     115  2135.3     127 2134.02
     135 2134.47   139.12133.647     147 2132.25     151 2132.45   154.32134.179
     163 2142.68     167 2144.65     223 2151.27     243 2155.08     255 2159.21
     279 2169.74     327  2192.2   372.1 2215.52   379.9 2220.16     391 2227.77
     395 2229.18     411 2233.32   431.4 2237.21   463.1 2244.62   532.2 2263.43
#Mann= 4 ,-1 , 0
       0     .06       0   13.54      .1       0   139.1    .045       0
   154.3      .1       0
Bank Sta=139.1,154.3
XS Rating Curve= 0 ,0
Exp/Cntr(USF)=0,0
Exp/Cntr=0.3,0.1

Type RM Length L Ch R = 1 ,8559    ,96.6,94.8,92.6
XS GIS Cut Line= 2
     2421130.434570260.8998355052421166.56443207570797.320913587
#Sta/Elev= 30
       0 2159.51      10 2159.36      18 2158.47      22 2156.76    42.1 2141.64
    46.1  2139.3    70.1 2130.16    74.2 2129.89    90.2 2131.58    94.2 2131.27
    99.62129.928   106.2 2129.45     1142129.777   146.3 2135.15   186.4 2143.89
   214.5 2148.22   246.5 2156.16   278.6 2168.41   314.7 2184.24   322.7 2188.39
   350.8 2198.85   362.9 2202.39   374.8 2207.87   382.9 2210.72   394.9 2215.94
   406.9 2222.41   441.6 2236.88   499.1 2255.41   527.2 2266.11   537.6 2270.68
#Mann= 4 ,-1 , 0
       0     .06       0    6.16      .1       0    99.6    .045       0
     114      .1       0
Bank Sta=99.6,114
XS Rating Curve= 0 ,0
Exp/Cntr=0.3,0.1

Type RM Length L Ch R = 1 ,8464    ,68.1,69,69.4
XS GIS Cut Line= 2
2421018.98863792570272.9963102142421142.69036619570792.543568918
#Sta/Elev= 30
       0 2155.07      18 2154.63    22.5  2153.2    51.3 2131.95    55.4 2129.47
    59.5 2128.14    71.8  2127.5    87.7 2128.48   108.9 2128.14   122.72125.523
   129.4 2124.46   138.12125.293   154.1 2133.71   166.4 2138.25   252.8 2154.95
   269.2 2160.14   300.3 2173.26   326.8 2186.01   355.6 2197.97   375.3 2204.12
   393.3 2212.28     409 2222.09   417.2 2225.67   433.7 2236.27   449.7 2248.12
     453 2249.61   466.6 2252.76   482.9 2254.33   499.8 2258.21   534.1 2268.98
#Mann= 4 ,-1 , 0
       0     .06       0   11.33      .1       0   122.7    .045       0
   138.1      .1       0
Bank Sta=122.7,138.1
XS Rating Curve= 0 ,0
Exp/Cntr(USF)=0,0
Exp/Cntr=0.3,0.1

Type RM Length L Ch R = 1 ,8395    ,105,107,108.6
XS GIS Cut Line= 2
2420959.19946926 570285.36648304     2421056.413      570819.893
#Sta/Elev= 30
       0  2153.6    13.7 2152.77    17.8 2151.44      25 2147.19    38.1 2136.86
    50.3  2132.4    62.5 2128.97    82.9  2126.3    97.2 2126.46   115.4 2125.12
   123.8 2123.12   127.6 2122.81     1392123.031   143.8 2123.74     156 2130.81
   168.2 2135.52   184.5 2138.55   196.7 2139.07   225.2 2142.46   249.6 2147.71
   257.7 2150.45   265.8 2154.35   294.3 2165.74     339 2187.85   380.1 2209.36
   393.1 2214.45     424  2230.3     461 2245.95   521.9 2276.09   543.3 2285.44
#Mann= 4 ,-1 , 0
       0     .06       0    8.25      .1       0   123.8    .045       0
     139      .1       0
Bank Sta=123.8,139
XS Rating Curve= 0 ,0
Exp/Cntr=0.3,0.1

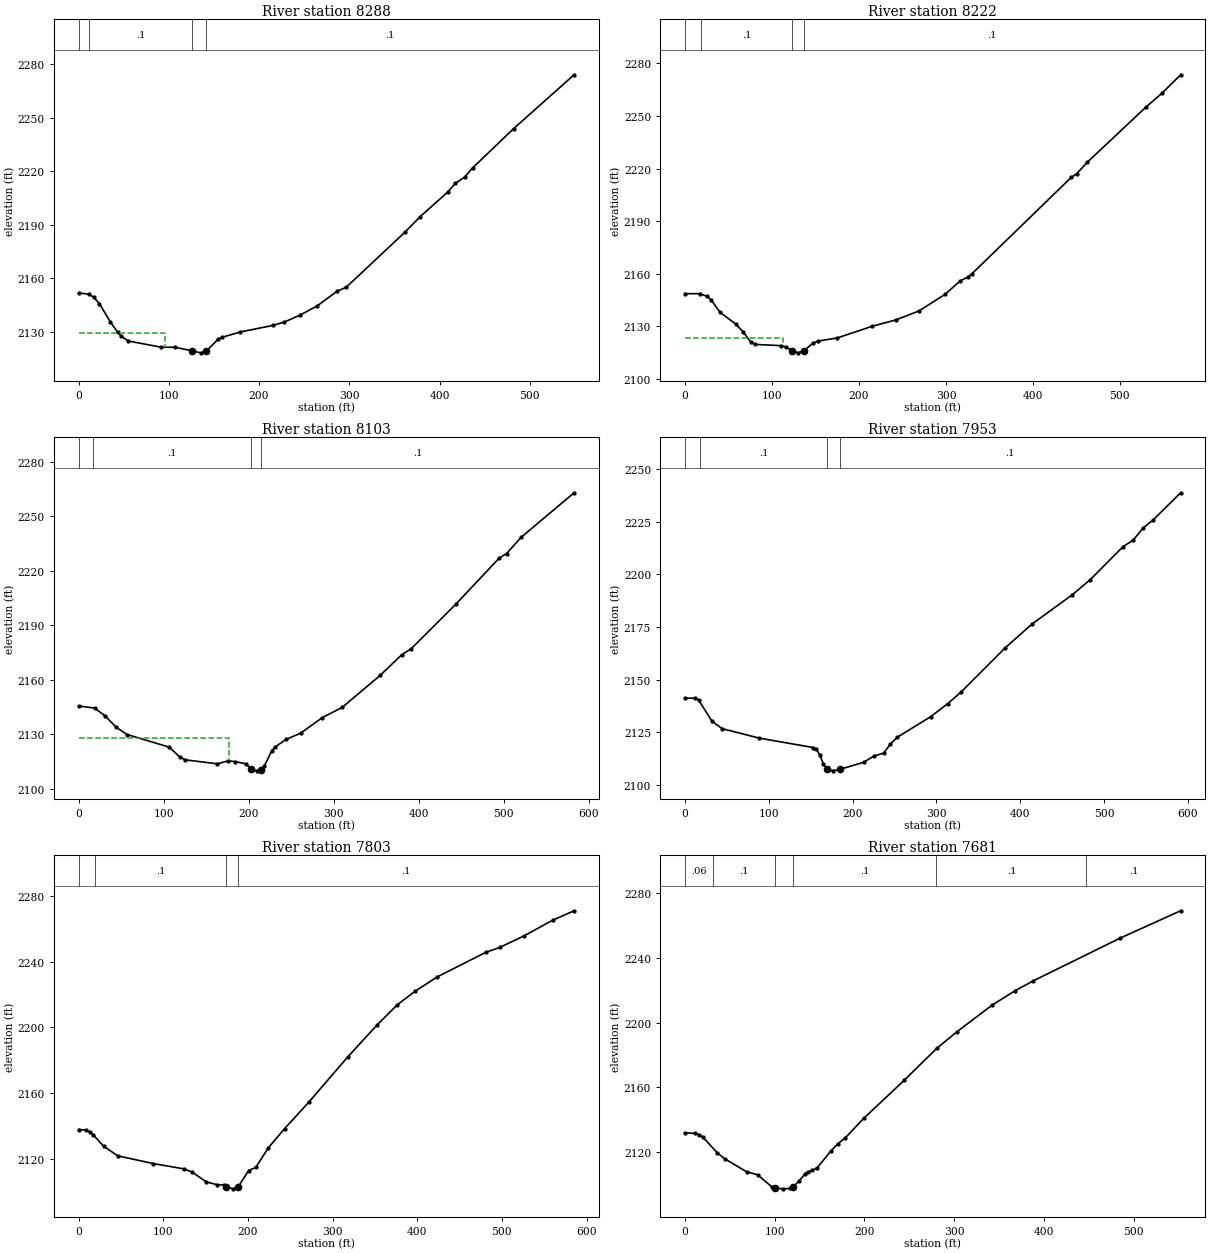
Type RM Length L Ch R = 1 ,8288    ,72.9,65.9,63
XS GIS Cut Line= 3
2420872.60825948570295.6749603952420880.85504136570518.338071268
2421002.42824674570821.011225912
#Sta/Elev= 30
       0 2151.83    11.2 2151.17    16.7 2149.48    23.2 2145.74    35.2 2135.63
    43.2 2129.89    47.2 2127.57    55.3 2124.84    91.3 2121.43   107.3 2121.32
   126.22119.327   135.3 2118.23   141.42119.119   154.9 2126.01   159.3 2126.98
   179.3 2129.95   215.4  2133.6   227.8 2135.47     245 2139.26   264.7 2144.66
   286.2 2152.67   296.7 2155.07   361.4  2185.8   378.6 2194.67   408.8 2208.27
   417.4 2213.28   427.7 2216.74   436.5 2221.89     482 2243.97     549 2274.17
#Mann= 4 ,-1 , 0
       0     .06       0   11.44      .1       0   126.2    .045       0
   141.4      .1       0
#XS Ineff= 2 , 0
           95.36  2129.6
Permanent Ineff=
       F       F
Bank Sta=126.2,141.4
XS Rating Curve= 0 ,0
Exp/Cntr=0.3,0.1

Type RM Length L Ch R = 1 ,8222    ,119.5,118.5,122.2
XS GIS Cut Line= 3
2420750.96822669570308.0451332212420864.36147759570522.461462211
2420988.06320586570825.530696455
#Sta/Elev= 30
       0 2148.66    16.8 2148.69    25.8 2147.09    30.4 2144.83    40.4 2137.96
    58.2  2131.4    66.6 2126.99    75.6 2121.11    80.1 2119.77   110.8 2119.03
   116.3 2118.25   123.42116.132   129.9 2114.95   136.2 2116.03     147 2120.38
   152.5 2121.61   175.2 2123.48     215 2130.07   242.6 2133.76   268.9 2138.82
   299.2 2148.36   316.5 2156.04   325.1 2158.08   329.4 2159.78   444.1    2215
   450.4 2217.08   462.5  2223.6     530 2255.07   548.5 2263.03   569.9  2273.5
#Mann= 4 ,-1 , 0
       0     .06       0   18.84      .1       0   123.4    .045       0
   136.2      .1       0
#XS Ineff= 2 , 0
          112.17 2123.18
Permanent Ineff=
       F       F
Bank Sta=123.4,136.2
XS Rating Curve= 0 ,0
Exp/Cntr(USF)=0,0
Exp/Cntr=0.3,0.1

Type RM Length L Ch R = 1 ,8103    ,149,150.9,153.6
XS GIS Cut Line= 2
2420672.18104946 570321.043930252420868.87648152570869.693827174
#Sta/Elev= 30
       0 2145.64      19 2144.47    31.7 2139.96    44.5 2133.82    57.2 2129.89
   106.7 2122.96   119.2 2117.47   125.4 2115.96   163.4 2113.77   176.2 2115.42
   184.3 2114.95   197.4 2113.71   203.12110.796   210.2  2109.9     2152110.464
   218.7 2112.73   227.2 2120.91   231.4 2123.12   244.2 2127.23   261.2 2130.63
   286.7 2139.22     310  2144.8   354.7 2162.45   380.1 2173.85   391.3 2177.19
   444.5 2202.06   494.9 2227.17   503.4 2229.58   520.4 2238.49   582.8 2263.06
#Mann= 4 ,-1 , 0
       0     .06       0   17.37      .1       0   203.1    .045       0
     215      .1       0
#XS Ineff= 2 , 0
          176.76 2128.19
Permanent Ineff=
       F       F
Bank Sta=203.1,215
XS Rating Curve= 0 ,0
Exp/Cntr=0.3,0.1

Type RM Length L Ch R = 1 ,7953    ,144.2,149.7,153.2
XS GIS Cut Line= 2
2420577.78580712570334.847174345     2420636.258      570923.474
#Sta/Elev= 30
       0 2141.24    12.1 2141.16    16.1 2140.38    32.2  2130.2    44.3 2126.75
    88.5 2122.25   152.8 2117.79   156.8 2116.86   160.8 2114.27   164.9 2110.19
   169.52107.465   176.9 2106.72   184.82107.419   213.1 2110.78   225.1 2113.68
   237.2 2115.16   245.2 2119.53   253.2 2122.65   293.5 2132.51   313.6 2138.65
   329.7 2144.21   381.9 2165.03     414 2176.36   462.3 2190.32   483.6 2197.46
   522.6 2213.06   534.8 2216.22   546.7 2221.94   558.8 2225.85   591.5  2238.7
#Mann= 4 ,-1 , 0
       0     .06       0   17.94      .1       0   169.5    .045       0
   184.8      .1       0
Bank Sta=169.5,184.8
XS Rating Curve= 0 ,0
Exp/Cntr=0.3,0.1

Type RM Length L Ch R = 1 ,7803    ,123.2,122.1,119.2
XS GIS Cut Line= 2
2420505.17314661570346.3927735192420337.63748003570907.106240016
#Sta/Elev= 30
       0 2138.14     8.9 2137.72      13 2136.82    17.2 2135.04    29.7 2127.98
    46.4 2122.16    88.2  2117.5   124.5 2114.26   134.1 2112.36   150.8 2106.39
   163.3  2104.7   171.7 2104.48   174.42103.513   182.4 2102.16   188.12103.018
   200.9 2113.26   209.3 2115.13   224.1    2127   243.4 2138.69   272.4 2154.99
   317.8 2182.08   352.7 2201.61   376.2 2213.67   397.1 2221.85   423.4 2230.63
   480.6  2245.5   497.4 2248.56   526.3 2255.61   559.9 2265.06   585.2 2270.78
#Mann= 4 ,-1 , 0
       0     .06       0   19.55      .1       0   174.4    .045       0
   188.1      .1       0
Bank Sta=174.4,188.1
XS Rating Curve= 0 ,0
Exp/Cntr=0.3,0.1

Type RM Length L Ch R = 1 ,7681    ,193.5,188.2,183.2
XS GIS Cut Line= 2
2420369.55519995570355.7445734392420258.89209341570897.024293353
#Sta/Elev= 30
       0    2132    11.4 2131.52    15.5 2130.87    19.5 2129.47    35.9 2119.57
      44 2115.94    68.5 2107.87    80.8 2105.98    97.1 2098.35   100.72097.779
   109.4 2097.29   116.9 2097.54   119.92098.312   127.1 2102.06   133.9 2106.63
   137.2 2107.88     142 2108.63   147.4 2110.37   162.4 2120.54   170.6 2125.25
   178.8 2128.89   199.2 2140.89   244.1 2164.28   280.8 2184.23   303.3 2194.49
   342.1 2210.78   367.7  2219.7   388.1 2225.84     485 2252.27   552.5 2269.19
#Mann= 6 ,-1 , 0
       0     .06       0   31.19      .1       0   100.7    .045       0
   119.9      .1       0  280.24      .1       0  447.36      .1       0
Bank Sta=100.7,119.9
XS Rating Curve= 0 ,0
Exp/Cntr=0.3,0.1

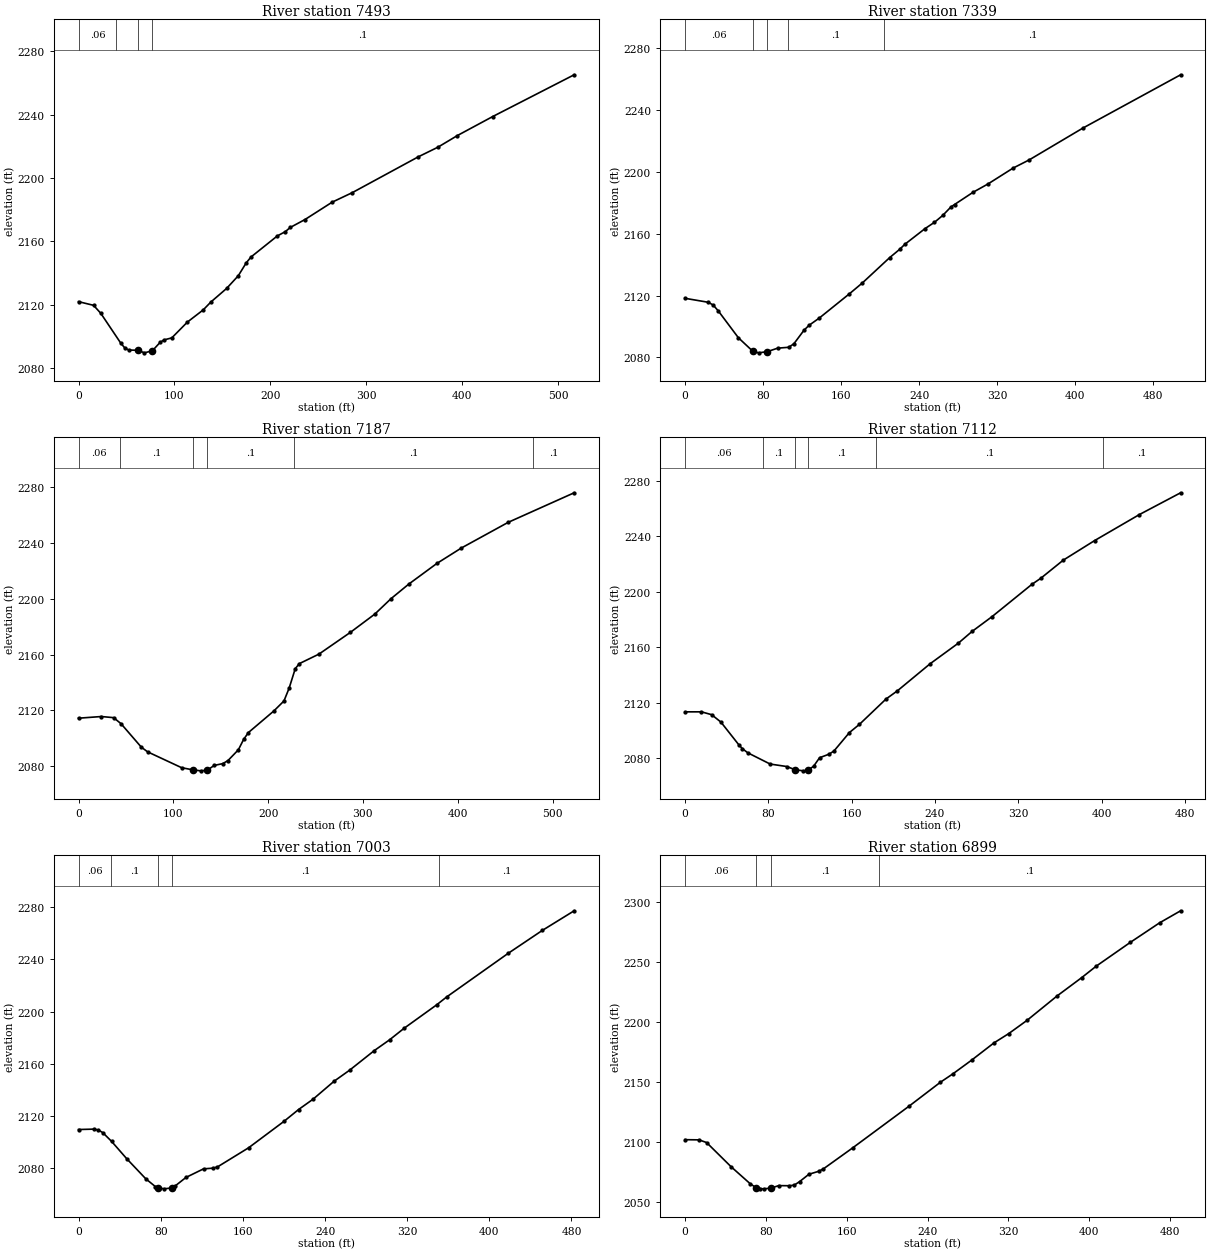
Type RM Length L Ch R = 1 ,7493    ,160.3,153.7,147.7
XS GIS Cut Line= 2
2420150.91934669 570379.511040072420251.19156004570886.206480032
#Sta/Elev= 30
       0 2121.84    15.7 2119.51    23.2 2114.47    44.2 2095.47    48.3 2092.54
    52.4 2091.25    61.82091.117    68.7 2089.49      772090.813      85 2096.09
    89.1 2097.66    97.2 2098.94   113.5 2108.95   129.9  2116.6     138 2121.64
   154.3 2130.17   166.5  2138.2   174.7 2146.28   179.7 2150.02   207.3 2163.41
   215.5 2166.06   220.6  2168.7   235.9 2173.68   264.4 2184.72   285.3 2190.71
   354.1 2213.35   374.5 2219.42   394.9 2226.81   431.6 2238.78   516.5 2265.18
#Mann= 4 ,-1 , 0
       0     .06       0   39.35      .1       0    61.8    .045       0
      77      .1       0
Bank Sta=61.8,77
XS Rating Curve= 0 ,0
Exp/Cntr=0.3,0.1

Type RM Length L Ch R = 1 ,7339    ,151.7,152.3,150.8
XS GIS Cut Line= 3
 2419979.4529334570452.467826722 2420139.5930517570648.039333352
2420221.22542669570890.109666711
#Sta/Elev= 30
       0 2118.24      24 2115.65      29 2113.83    34.2 2110.04    54.8 2092.68
    69.52084.008    75.5 2082.95    84.52083.744      95 2085.97   106.4 2086.55
   111.7 2088.84     122 2097.56   127.2 2100.76   137.7 2105.45   168.6 2121.15
     182 2128.24   209.9 2144.58   220.3 2150.02   225.4 2153.17   246.1 2163.32
   255.8 2167.41   264.2 2171.82   272.7 2177.35   276.4 2178.93   295.4 2186.85
   310.7 2192.23   336.4 2202.49   352.9 2207.78   407.7 2228.28   508.2 2262.87
#Mann= 5 ,-1 , 0
       0     .06       0    69.5    .045       0    84.5     .06       0
  105.68      .1       0   204.5      .1       0
Bank Sta=69.5,84.5
XS Rating Curve= 0 ,0
Exp/Cntr=0.3,0.1

Type RM Length L Ch R = 1 ,7187    ,73,74.8,75.9
XS GIS Cut Line= 2
2419874.06729199570549.5109067912420223.17294666570938.668293353
#Sta/Elev= 30
       0  2114.4    24.1  2115.6      37 2114.79    44.8 2110.49    66.3 2093.59
    72.9 2090.26   108.8 2078.88   120.7 2077.35   128.9 2076.64   135.92077.138
   143.1 2080.51   152.3 2081.85   157.7 2084.05   168.6 2091.74   174.2 2099.22
   179.2  2104.1   206.1 2119.63   216.7 2126.76   222.2 2136.03   228.6 2149.91
   232.9 2153.54   253.6 2160.37   286.7 2175.94   312.5 2189.06   329.6 2200.13
   348.4 2210.62     378 2225.42   403.7 2236.43   453.2 2254.89   522.8  2276.1
#Mann= 6 ,-1 , 0
       0     .06       0   43.49      .1       0   120.7    .045       0
   135.9      .1       0  227.41      .1       0  479.05      .1       0
Bank Sta=120.7,135.9
XS Rating Curve= 0 ,0
Exp/Cntr=0.3,0.1

Type RM Length L Ch R = 1 ,7112    ,105.3,109,111.2
XS GIS Cut Line= 2
2419835.65790536570597.9401334062420109.53353173570987.043919657
#Sta/Elev= 30
       0 2113.27    15.8 2113.28    25.6 2111.23    34.5 2105.88    51.7 2089.47
      55 2086.76    60.3  2083.7    81.8 2075.58    97.6 2073.82     1062071.442
   113.7 2070.69     1182071.107   123.5 2074.02   129.2 2080.16   138.1 2082.66
     143    2085   157.9 2098.36   167.5 2104.26     193 2122.54   203.9 2128.44
   235.4 2148.03   262.5  2162.9   275.6 2171.32   294.7 2181.96     333 2205.29
   341.7 2209.77   363.1 2222.75   393.3 2236.93   436.2 2255.67   475.8  2271.4
#Mann= 6 ,-1 , 0
       0     .06       0   74.67      .1       0     106    .045       0
     118      .1       0  183.46      .1       0  401.06      .1       0
Bank Sta=106,118
XS Rating Curve= 0 ,0
Exp/Cntr(USF)=0,0
Exp/Cntr=0.3,0.1

Type RM Length L Ch R = 1 ,7003    ,106.6,103.4,100.9
XS GIS Cut Line= 3
 2419768.8589721570644.6993866892419815.61822538570771.617359887
2420022.69491849571050.502906256
#Sta/Elev= 30
       0 2109.58    15.1  2109.9    19.4 2109.17    23.6 2107.22    32.2  2100.5
    46.8 2087.34    65.5 2071.81    74.8 2065.87    77.22065.057    83.3 2064.12
    90.72064.806    93.5 2065.95   104.6 2072.85   121.7 2079.43   130.9 2079.97
   135.3 2080.92   165.6 2095.58   199.9 2115.75   214.3 2124.93   228.5 2132.91
   248.9 2146.64   263.9 2155.03   288.1 2170.15   302.8  2178.3   317.1 2187.24
   348.6 2205.08   358.5 2211.23   418.3  2244.6   451.5 2262.15   482.6 2277.25
#Mann= 5 ,-1 , 0
       0     .06       0   31.61      .1       0    77.2    .045       0
    90.7      .1       0  351.08      .1       0
Bank Sta=77.2,90.7
XS Rating Curve= 0 ,0
Exp/Cntr(USF)=0,0
Exp/Cntr=0.3,0.1

Type RM Length L Ch R = 1 ,6899    ,147,147.9,148.8
XS GIS Cut Line= 2
2419666.99059887570713.168293283     2419940.632      571120.115
#Sta/Elev= 30
       0 2101.73    13.9 2101.58    21.4 2099.34    45.5 2079.26    64.7 2064.84
    70.32061.743    74.4 2060.87    78.4 2060.72    85.6 2061.43    92.7 2063.41
   103.3 2063.31   108.1 2063.81   113.5 2066.81   122.6 2072.87   132.2 2075.33
     137 2077.41     166 2094.94   221.8 2129.75   252.7 2149.64   264.8 2156.49
   283.5 2168.01   305.7 2182.47   320.2 2190.16   338.3 2201.19   368.4  2221.8
   392.5 2236.91     407 2246.57   440.7 2266.38   469.6 2282.64   490.4 2292.69
#Mann= 4 ,-1 , 0
       0     .06       0    70.3    .045       0    85.6      .1       0
  192.15      .1       0
Bank Sta=70.3,85.6
XS Rating Curve= 0 ,0
Exp/Cntr=0.3,0.1

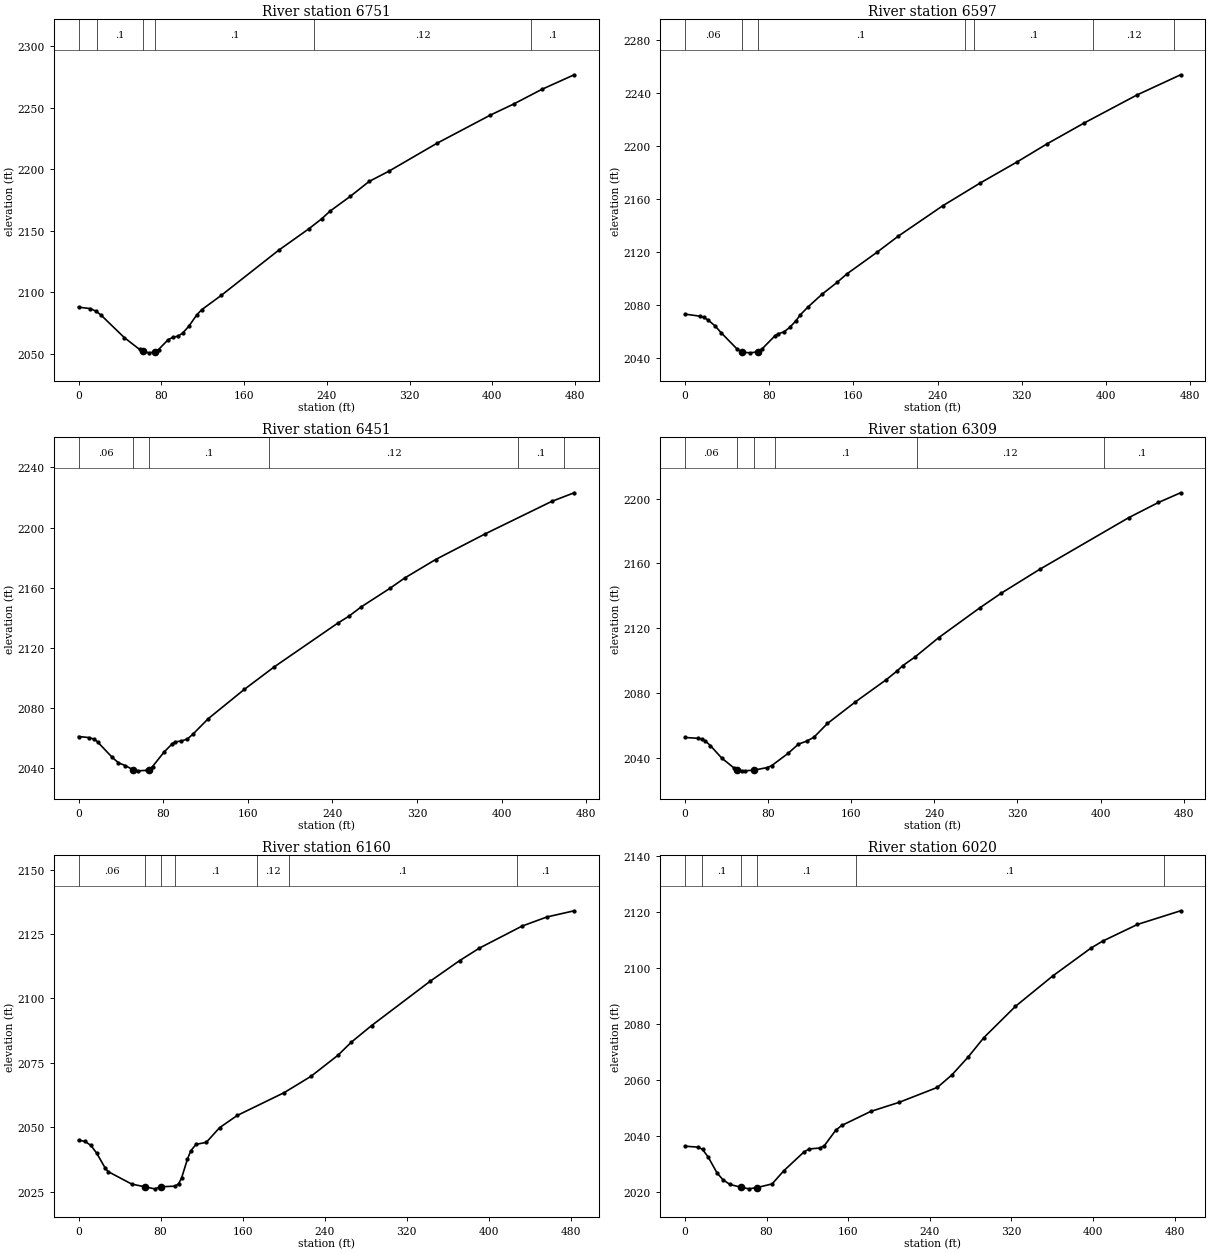
Type RM Length L Ch R = 1 ,6751    ,156,154,152.2
XS GIS Cut Line= 2
2419548.93356004570792.052960064     2419790.854      571205.525
#Sta/Elev= 30
       0  2088.1    11.5 2086.91    17.2 2084.66    21.8 2081.62    44.3 2063.37
      59 2053.79    62.12052.325    68.2 2051.02    73.82051.802    77.4 2053.73
    86.7 2061.76    91.1 2063.56      96 2064.59   100.6 2066.96   106.6 2072.62
   114.5 2082.04   119.1 2086.06   137.9 2097.63   193.4 2134.28   222.7 2151.76
     235 2159.81   243.1 2166.06   262.8 2178.12   280.8  2190.1   299.9 2198.43
   346.2 2221.02   398.1 2244.02   420.4 2252.92   447.8 2264.89     479 2276.71
#Mann= 6 ,-1 , 0
       0     .06       0   17.92      .1       0    62.1    .045       0
    73.8      .1       0  227.56     .12       0   437.2      .1       0
Bank Sta=62.1,73.8
XS Rating Curve= 0 ,0
Exp/Cntr=0.3,0.1

Type RM Length L Ch R = 1 ,6597    ,147.8,147,146.1
XS GIS Cut Line= 2
2419415.45566671570885.870720048       2419712.9      571250.901
#Sta/Elev= 30
       0 2073.19    14.4 2071.63    17.9 2070.72      22 2068.71    28.7 2064.22
    34.3  2059.2    49.5 2046.87    53.92044.478    62.2 2043.98    68.92044.774
    73.6 2047.23    85.5 2056.85    88.4 2058.25    94.2 2059.85    99.7 2063.32
   105.4 2068.15   109.7 2072.77   116.8 2078.52   130.3 2088.26   144.5 2097.12
   153.7 2103.46   182.2 2119.73   202.5 2131.94   244.7 2154.84   279.9 2171.85
   315.5 2188.01   344.2 2201.76   378.8  2217.2   429.5 2238.57   470.9 2253.78
#Mann= 7 ,-1 , 0
       0     .06       0    53.9    .045       0    68.9      .1       0
  265.79     .12       0  274.66      .1       0  387.67     .12       0
  464.64      .1       0
Bank Sta=53.9,68.9
XS Rating Curve= 0 ,0
Exp/Cntr=0.3,0.1

Type RM Length L Ch R = 1 ,6451    ,144.2,141.5,139.4
XS GIS Cut Line= 2
2419308.53564004570991.689666711     2419628.024      571334.469
#Sta/Elev= 30
       0 2061.13     9.8 2060.45      15 2059.31      18 2057.57    31.7 2047.39
    37.8 2043.64    44.3  2041.8    51.22039.155      56 2038.32    64.5 2038.64
    66.42039.114      70 2041.19    80.9 2050.82    88.7 2056.36    91.6 2057.58
    97.3 2058.15     103 2059.51   108.3 2062.78   122.7 2073.02   156.7 2092.42
   185.1 2107.44     245 2136.44   255.5 2141.03   267.2 2147.25   294.2 2159.52
   308.3 2166.45   337.6 2178.76   384.6 2195.86   447.3 2217.38   468.6 2223.13
#Mann= 6 ,-1 , 0
       0     .06       0    51.2    .045       0    66.4      .1       0
  179.92     .12       0  415.63      .1       0   459.1     .12       0
Bank Sta=51.2,66.4
XS Rating Curve= 0 ,0
Exp/Cntr=0.3,0.1

Type RM Length L Ch R = 1 ,6309    ,145.2,149,152
XS GIS Cut Line= 2
2419199.11769338571097.071666711     2419581.894      571381.613
#Sta/Elev= 30
       0 2052.38    12.5 2051.88    16.5 2051.28    19.5 2050.31    24.5 2047.33
    35.3  2039.7    46.8 2033.71    49.92032.466    54.4 2031.79    58.2 2031.76
    66.72032.252    79.3  2033.8    83.5    2035    99.2 2042.54   109.2 2048.27
     117  2050.1     124 2052.46   137.1 2061.03   164.1 2074.41   193.9 2088.19
   204.2 2093.55   209.7 2096.85   221.2 2102.04     244 2114.01   283.6 2132.46
   304.1 2141.47   341.2 2156.26     427 2188.25   455.6 2197.65     477 2203.65
#Mann= 6 ,-1 , 0
       0     .06       0    49.9    .045       0    66.7     .06       0
   86.37      .1       0  223.21     .12       0  403.02      .1       0
Bank Sta=49.9,66.7
XS Rating Curve= 0 ,0
Exp/Cntr=0.3,0.1

Type RM Length L Ch R = 1 ,6160    ,142.1,139.7,136.4
XS GIS Cut Line= 2
2419112.73658671571188.097986733     2419406.951      571571.315
#Sta/Elev= 30
       0 2044.94     6.3 2044.47      12 2042.94    17.7 2039.92    26.2 2033.97
    29.1 2032.69    51.9 2027.88    65.22026.795    74.1 2026.04    80.52026.842
    94.3 2027.09    97.6 2028.07   100.4 2030.19   106.1  2037.5   109.4  2040.8
   114.5  2043.3   124.6 2044.12   137.5 2049.81   154.8 2054.57   200.4 2063.41
   226.6 2069.76   252.9 2077.95     266 2083.06   285.7 2089.49   342.9 2106.75
   371.4  2114.7   390.8 2119.59   432.2 2128.11   456.5 2131.67   483.1 2134.08
#Mann= 7 ,-1 , 0
       0     .06       0    65.2    .045       0    80.5     .06       0
   93.93      .1       0  174.36     .12       0   205.1      .1       0
  427.44      .1       0
Bank Sta=65.2,80.5
XS Rating Curve= 0 ,0
Exp/Cntr=0.3,0.1

Type RM Length L Ch R = 1 ,6020    ,123.5,124.1,122.9
XS GIS Cut Line= 2
2419000.91856004 571292.46485339      2419375.32      571602.035
#Sta/Elev= 30
       0 2036.26    12.8 2035.92    17.2 2035.13    22.9 2032.27    31.4  2026.7
    37.1  2024.3    43.9 2022.58    54.92021.552    62.7 2020.99    70.72021.459
    85.4 2022.75    96.8 2027.44   116.6 2034.19   121.7 2035.26   132.1  2035.6
   136.6 2036.44   147.7 2041.94   153.6 2043.67     182 2048.69     210 2051.97
   247.4 2057.31   261.6 2061.77   277.5 2068.16     293 2075.15   323.9 2086.32
   360.5 2097.21   397.9 2107.17   409.3 2109.65   443.5 2115.64   485.8 2120.53
#Mann= 6 ,-1 , 0
       0     .06       0   16.88      .1       0    54.9    .045       0
    70.7      .1       0  167.65      .1       0  469.19      .1       0
Bank Sta=54.9,70.7
XS Rating Curve= 0 ,0
Exp/Cntr=0.3,0.1