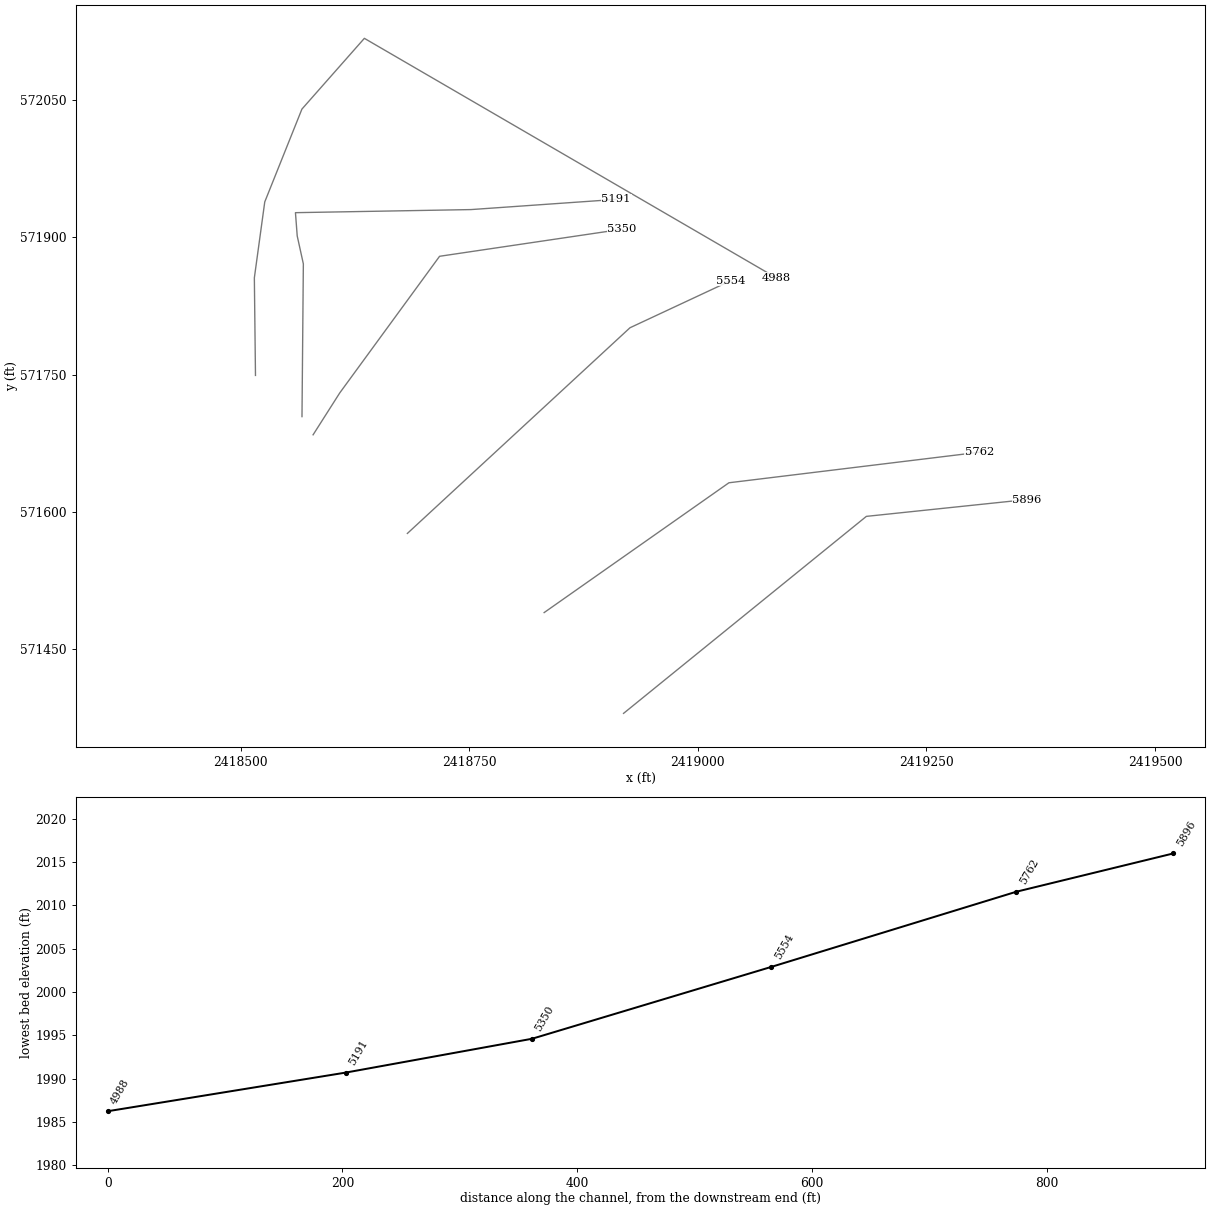
HEC-RAS study SBPOTOMC_T6.prj: SBPOTOMC_T6

--- SBPOTOMC_T6.g01 (geometry) --- (continued)

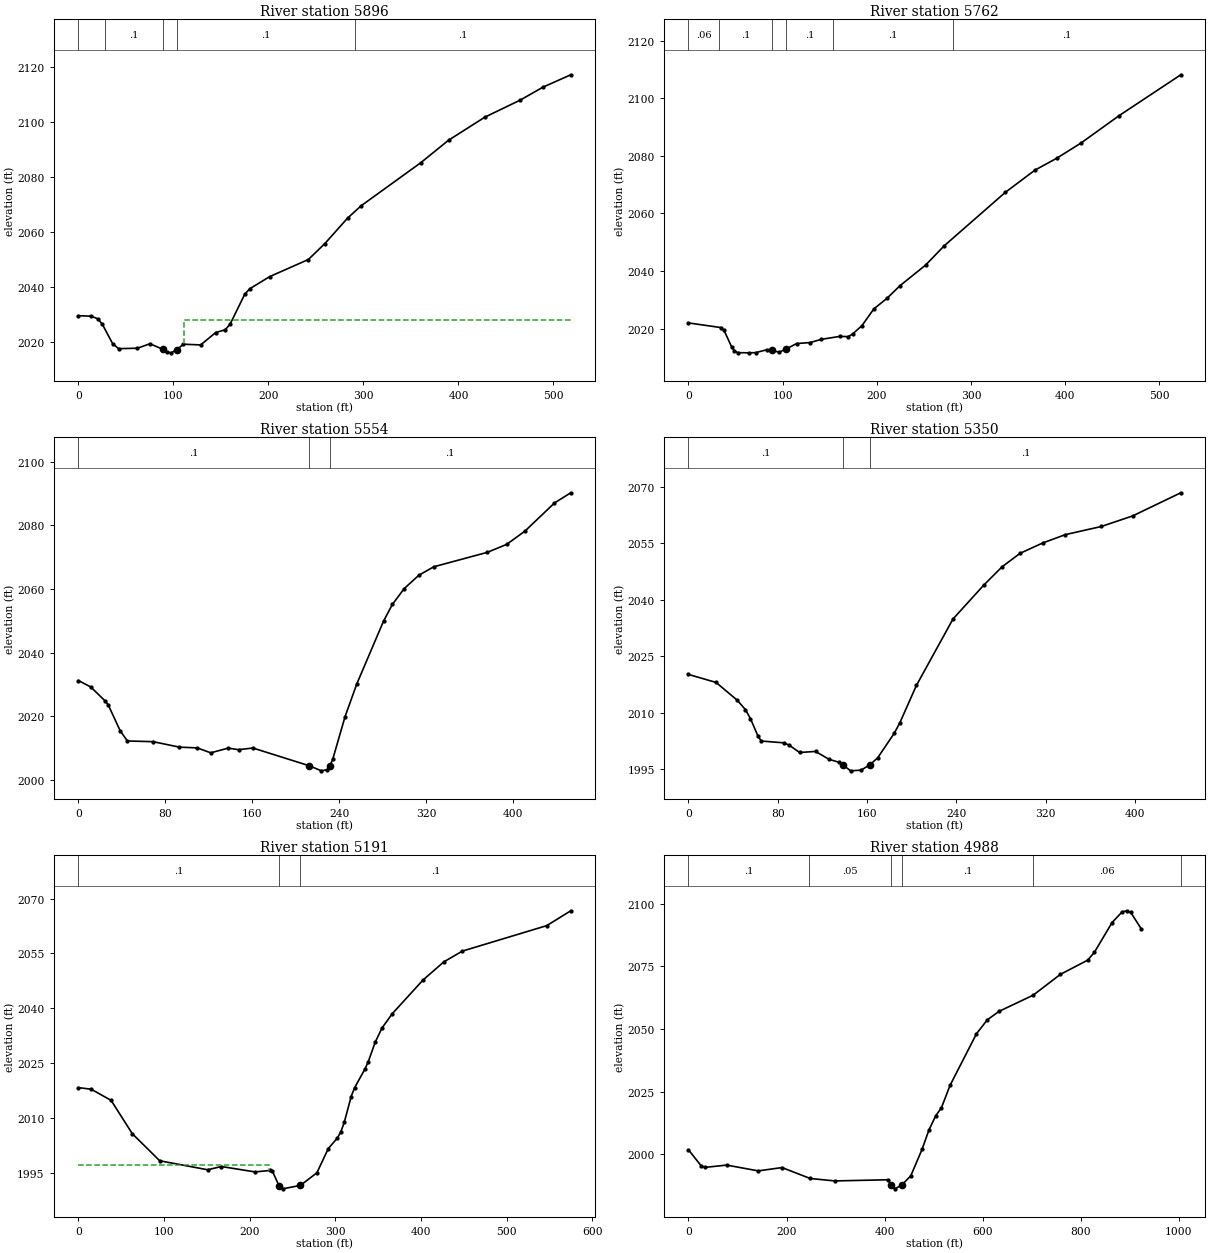
Type RM Length L Ch R = 1 ,5896    ,134.7,133.9,133.1
XS GIS Cut Line= 3
2418918.84254634571379.4876525712419184.36830605571594.914212341
2419359.71550587571613.283918988
#Sta/Elev= 30
       0 2029.52    13.7 2029.32    20.5 2028.35    25.1  2026.4    35.9 2019.39
    42.2 2017.52    62.1 2017.68    75.2  2019.3    88.7 2017.31    93.3 2016.25
    97.7    2016   103.8  2017.2   110.4 2019.14   128.6 2018.88   144.5  2023.4
   154.4 2024.39   159.6 2026.44     175  2037.3   180.2  2039.3   201.4 2043.75
     242 2049.96   259.4 2055.77   283.2    2065   297.4 2069.47   360.4  2085.2
   389.5 2093.35   427.8 2101.76     465 2107.96   489.1  2112.7   518.2 2117.17
#Mann= 5 ,-1 , 0
       0     .06       0   27.74      .1       0    88.7    .045       0
   103.8      .1       0  290.69      .1       0
#XS Ineff= 2 , 0
                          110.96         2028.11
Permanent Ineff=
       F       F
Bank Sta=88.7,103.8
XS Rating Curve= 0 ,0
Exp/Cntr(USF)=0,0
Exp/Cntr=0.3,0.1

Type RM Length L Ch R = 1 ,5762    ,206.9,208.6,211
XS GIS Cut Line= 3
 2418832.0039331571489.7058924532419034.07070622571631.653625635
2419307.94633259571665.053092266
#Sta/Elev= 30
       0 2021.96    34.4 2020.35    37.6 2019.48    45.9 2013.58    48.8 2012.28
    52.2 2011.64    64.7 2011.57    71.6 2011.65    83.2 2012.66    88.42012.453
    96.2 2011.79   103.42012.841   114.8  2014.8   129.2 2015.14   141.2 2016.27
   160.7 2017.28   169.6  2017.2   174.4 2018.14   184.2 2021.02   196.9 2026.85
   210.8 2030.51   224.7 2034.92   251.7 2042.02   271.5 2048.73   336.3 2067.27
   367.9 2075.03   390.9 2079.13   416.9 2084.46   457.2 2093.94   522.8 2108.15
#Mann= 6 ,-1 , 0
       0     .06       0   32.47      .1       0    88.4    .045       0
   103.4      .1       0  153.84      .1       0  280.97      .1       0
Bank Sta=88.4,103.4
XS Rating Curve= 0 ,0
Exp/Cntr(USF)=0,0
Exp/Cntr=0.3,0.1

Type RM Length L Ch R = 1 ,5554    ,201.8,203.8,205.6
XS GIS Cut Line= 3
2418682.46030523571576.2606830092418925.87613172571801.165000655
2419036.33673789571852.773992004
#Sta/Elev= 30
       0 2031.24    11.3 2029.23    24.7 2024.79    27.5 2023.52    38.5 2015.41
    45.1 2012.27    68.7 2012.05      93 2010.33   109.3  2010.1   121.8 2008.55
   137.9 2010.03   147.4 2009.53   160.6 2010.06   212.72004.463   223.7 2002.89
   229.1 2003.27   231.3 2004.26   234.2 2006.62   245.5 2019.95   256.3 2030.21
   280.9 2049.91     289 2055.14   299.9 2060.12   313.4 2064.32   327.1 2066.97
   376.5 2071.52   394.2    2074   411.1 2078.18   438.3 2087.02   453.3 2090.22
#Mann= 3 ,-1 , 0
       0      .1       0   212.7    .045       0   231.3      .1       0
Bank Sta=212.7,231.3
XS Rating Curve= 0 ,0
Exp/Cntr(USF)=0,0
Exp/Cntr=0.3,0.1

Type RM Length L Ch R = 1 ,5350    ,168.4,158.8,144.7
XS GIS Cut Line= 4
2418579.35681456571684.1161375892418608.52323441571729.938663276
2418717.66857512571879.3138948972418917.03226855571908.855962115
#Sta/Elev= 30
       0 2020.18    24.7 2018.05    43.6 2013.35      51 2010.84    55.5 2008.45
    62.3 2003.77    65.2  2002.5    85.2 2002.03    90.2 2001.41    99.5 1999.46
   113.8 1999.74   125.9 1997.64   134.8 1996.87   138.61996.066   145.3 1994.59
   154.6 1994.78   162.41996.188   169.4 1998.03   184.3 2004.58   189.3 2007.35
   204.1 2017.25   236.9  2034.9   264.5  2043.9   280.8 2048.73     297 2052.33
   317.2 2055.06   337.5 2057.28   369.8 2059.45   397.8 2062.25   440.9 2068.39
#Mann= 3 ,-1 , 0
       0      .1       0   138.6    .045       0   162.4      .1       0
Bank Sta=138.6,162.4
XS Rating Curve= 0 ,0
Exp/Cntr(USF)=0,0
Exp/Cntr=0.3,0.1

Type RM Length L Ch R = 1 ,5191    ,207.5,202.6,193.5
XS GIS Cut Line= 6
2418567.20963596571703.9860656032418568.70292096571871.024104191
2418561.99782341571901.5386630712418560.06261696571927.013274151
2418752.03847567571930.3926796272418910.84829052 571941.52822903
#Sta/Elev= 30
       0 2018.34    14.9  2017.9    38.1 2014.86    62.9 2005.74    94.9 1998.35
   150.9 1995.89   166.9 1996.78   206.3  1995.3   223.8 1995.71   226.5 1995.51
   234.2 1991.53   238.5 1990.68   259.3 1991.63   278.5 1995.07   291.8 2001.69
   302.5  2004.6   306.5 2006.27   310.5 2008.92   318.5  2015.9   322.5 2018.31
   334.5 2023.39   338.5 2025.43   346.5 2030.72   354.5 2034.63   366.5 2038.54
   402.5 2047.77   426.8 2052.72   448.4 2055.65   546.9 2062.61     575 2066.67
#Mann= 3 , 0 , 0
       0      .1       0   234.2    .045       0   259.3      .1       0
#XS Ineff= 2 , 0
          222.16 1997.09
Permanent Ineff=
       F       F
Bank Sta=234.2,259.3
XS Rating Curve= 0 ,0
Exp/Cntr(USF)=0,0
Exp/Cntr=0.3,0.1

Type RM Length L Ch R = 1 ,4988    ,466.8,467.9,469.9
XS GIS Cut Line= 6
2418516.35155883571749.0310576582418515.12191772571855.749911461
2418526.49564797571938.7707000952418567.13781837572040.273417122
2418635.42249499 572117.64552828       2419085.6       571855.92
#Sta/Elev= 30
       0  2001.8    25.9 1995.39    33.9 1994.79    77.9  1995.7   142.2 1993.39
   190.8 1994.71   248.3 1990.35   298.4 1989.38     407 1989.84   413.4 1987.79
   420.9 1986.22   434.8 1987.72   453.3 1991.38   476.4 2001.99   490.3 2009.65
   504.1 2015.34   515.9 2018.58   533.4  2027.5   587.4 2048.13   609.5  2053.7
   633.7 2057.09   703.1 2063.53   758.6 2071.84   814.2  2077.5     828 2080.68
     864 2092.53   884.5 2096.79   894.1 2097.21   902.1 2096.53   923.9 2089.85
#Mann= 6 ,-1 , 0
       0      .1       0   245.3     .05       0   413.4    .045       0
   434.8      .1       0   703.3     .06       0  1004.1      .1       0
Bank Sta=413.4,434.8
XS Rating Curve= 0 ,0
Exp/Cntr(USF)=0,0
Exp/Cntr=0.3,0.1
LCMann Table=0

Chan Stop Cuts=-1
Use User Specified Reach Order=0
Composite Channel Slope=5